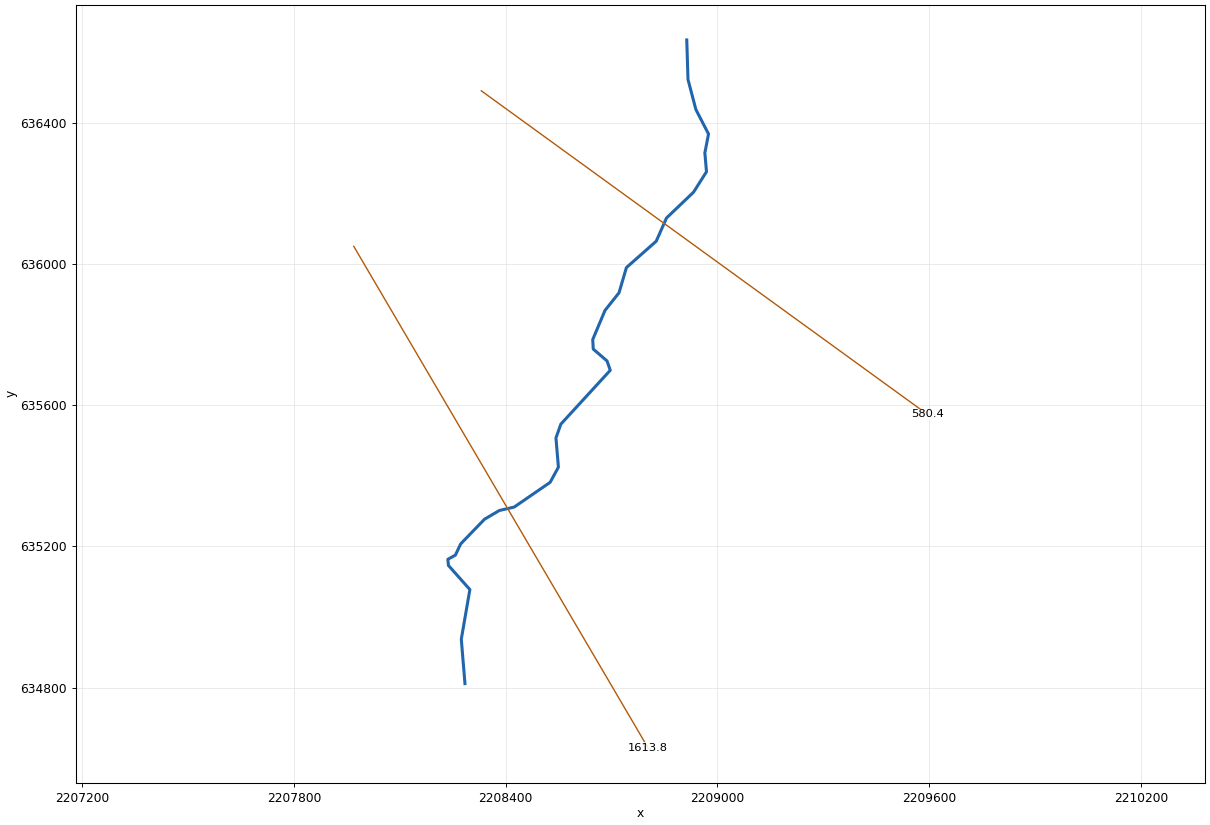
--- LICKRN2.prj (project) ---

Proj Title=LICKRN2
Current Plan=p01
Geom File=g01
Flow File=f01
Plan File=p01
DSS Export Rating Curves=0
DSS Export Rating Curve Sorted=0
DSS Export Volume Flow Curves=0
DXF OffsetX=0
DXF OffsetY=0
DXF ScaleX=0
DXF ScaleY=0

--- LICKRN2.p01 (plan) ---

Plan Title=Floodplain
Program Version=4.00
Geom File=g01
Flow File=f01
K Sum by GR=0
Std Step Tol=0.01
Critical Tol=0.01
Num of Std Step Trials=20
Max Error Tol=0.3
Flow Tol Ratio=0.001
Split Flow NTrial=30
Split Flow Tol=0.02
Split Flow Ratio=0.02
Log Output Level=0
Friction Slope Method=1
Unsteady Friction Slope Method=2
Unsteady Bridges Friction Slope Method=1
Global Log Level=0
CheckData=False
Run HTab=0
Run UNet=0
Run PostProcess=0
UNET Theta=0
UNET Theta Warmup=0
UNET ZTol=0
UNET ZSATol=0
UNET MxIter=0
UNET MaxInSteps=0
UNET DtIC=0
UNET DtMin=0
UNET MaxCRTS=0
UNET WFStab=0
UNET SFStab=0
UNET WFX=0
UNET SFX=0
UNET DSS MLevel=0
UNET DZMax Abort=0
UNET Convert EG Bridges=0
UNET Use Existing IB Tables=0
UNET Froude Limit=0
UNET Froude Power=0
Write IC File=0
Echo Input=False
Echo Output=False
Write Detailed=0

--- LICKRN2.f01 (steady flow) ---

Flow Title=Flow
Program Version=4.00
Number of Profiles=1
Profile Names=P100yr
River Rch & RM=LICKRN2,Main      ,1613.8
318.0870
River Rch & RM=LICKRN2,Main      ,1613.8
287.5440
River Rch & RM=LICKRN2,Main      ,580.4
335.8380
River Rch & RM=LICKRN2,Main      ,580.4
332.1162
River Rch & RM=LICKRN2,Main      ,580.4
329.7512
Boundary for River Rch & Prof#=LICKRN2,Main      ,1
Up Type=0
Dn Type=3
Dn Slope=0.050094

--- LICKRN2.g01 (geometry) ---

Geom Title=Geometry
Program Version=4.00

River Reach=LICKRN2     ,Main
Reach XY= 30
     2208284.912      634811.321     2208274.495      634937.190
     2208298.801      635077.815     2208238.095      635146.101
     2208236.407      635163.489     2208257.684      635175.250
     2208272.759      635207.155     2208340.273      635277.112
     2208382.310      635301.816     2208424.372      635311.551
     2208526.231      635381.634     2208549.703      635424.556
     2208542.725      635507.502     2208556.614      635546.565
     2208696.622      635699.142     2208687.447      635725.592
     2208648.457      635759.256     2208646.891      635786.148
     2208681.613      635868.613     2208721.433      635918.835
     2208742.377      635990.141     2208826.847      636064.864
     2208855.901      636130.589     2208932.482      636203.683
     2208969.283      636261.610     2208964.654      636315.174
     2208975.016      636368.638     2208939.193      636438.137
     2208916.857      636523.127     2208913.384      636635.106

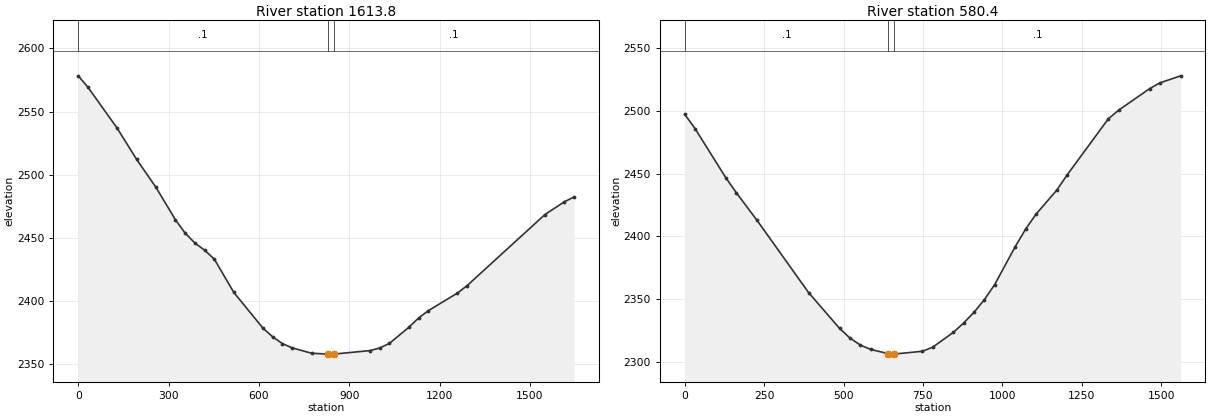
Type RM Length L Ch R = 1 ,1613.8,1019.8,1033.4,1040.9
XS GIS Cut Line= 2
     2207969.905      636050.205     2208803.238      634630.066
#Sta/Elev= 30
       0 2578.33    32.3 2569.31   129.1 2536.92   193.7 2512.18   258.3 2489.88
   322.9 2464.18   355.2 2453.63   387.4 2445.81   419.7 2440.12   452.0 2432.99
   516.6 2406.66   613.4 2378.33   645.7 2371.45   678.0 2366.05   710.3 2362.73
   774.9 2358.43   829.4 2357.78   839.4 2357.74   849.4 2357.76   968.6 2360.55
  1000.9 2362.60  1033.2 2366.22  1097.7 2379.01  1130.0 2386.34  1162.3 2392.15
  1259.2 2406.14  1291.4 2412.09  1549.7 2468.38  1614.3 2478.53  1646.6 2482.35
#Mann= 3 , 0 , 0
       0     0.1       0   829.4   0.045       0   849.4     0.1       0
Bank Sta=829.4,849.4
Exp/Cntr=0.3,0.1

Type RM Length L Ch R = 1 ,580.4,561.4,580.4,596
XS GIS Cut Line= 2
     2208331.016      636491.177     2209594.905      635574.511
#Sta/Elev= 30
       0 2497.34    32.5 2485.97   130.1 2446.48   162.6 2434.72   227.7 2412.74
   390.3 2355.01   487.9 2326.44   520.4 2318.77   553.0 2313.23   585.5 2309.72
   640.5 2306.40   650.6 2305.97   660.5 2306.06   748.1 2308.24   780.7 2311.49
   845.7 2323.30   878.2 2330.79   910.8 2339.33   943.3 2349.35   975.8 2361.42
  1040.9 2391.84  1073.4 2405.72  1105.9 2417.58  1171.0 2436.69  1203.5 2448.74
  1333.6 2493.69  1366.2 2500.59  1463.7 2517.78  1496.3 2522.41  1561.3 2528.01
#Mann= 3 , 0 , 0
       0     0.1       0   640.5   0.045       0   660.5     0.1       0
Bank Sta=640.5,660.5
Exp/Cntr=0.3,0.1