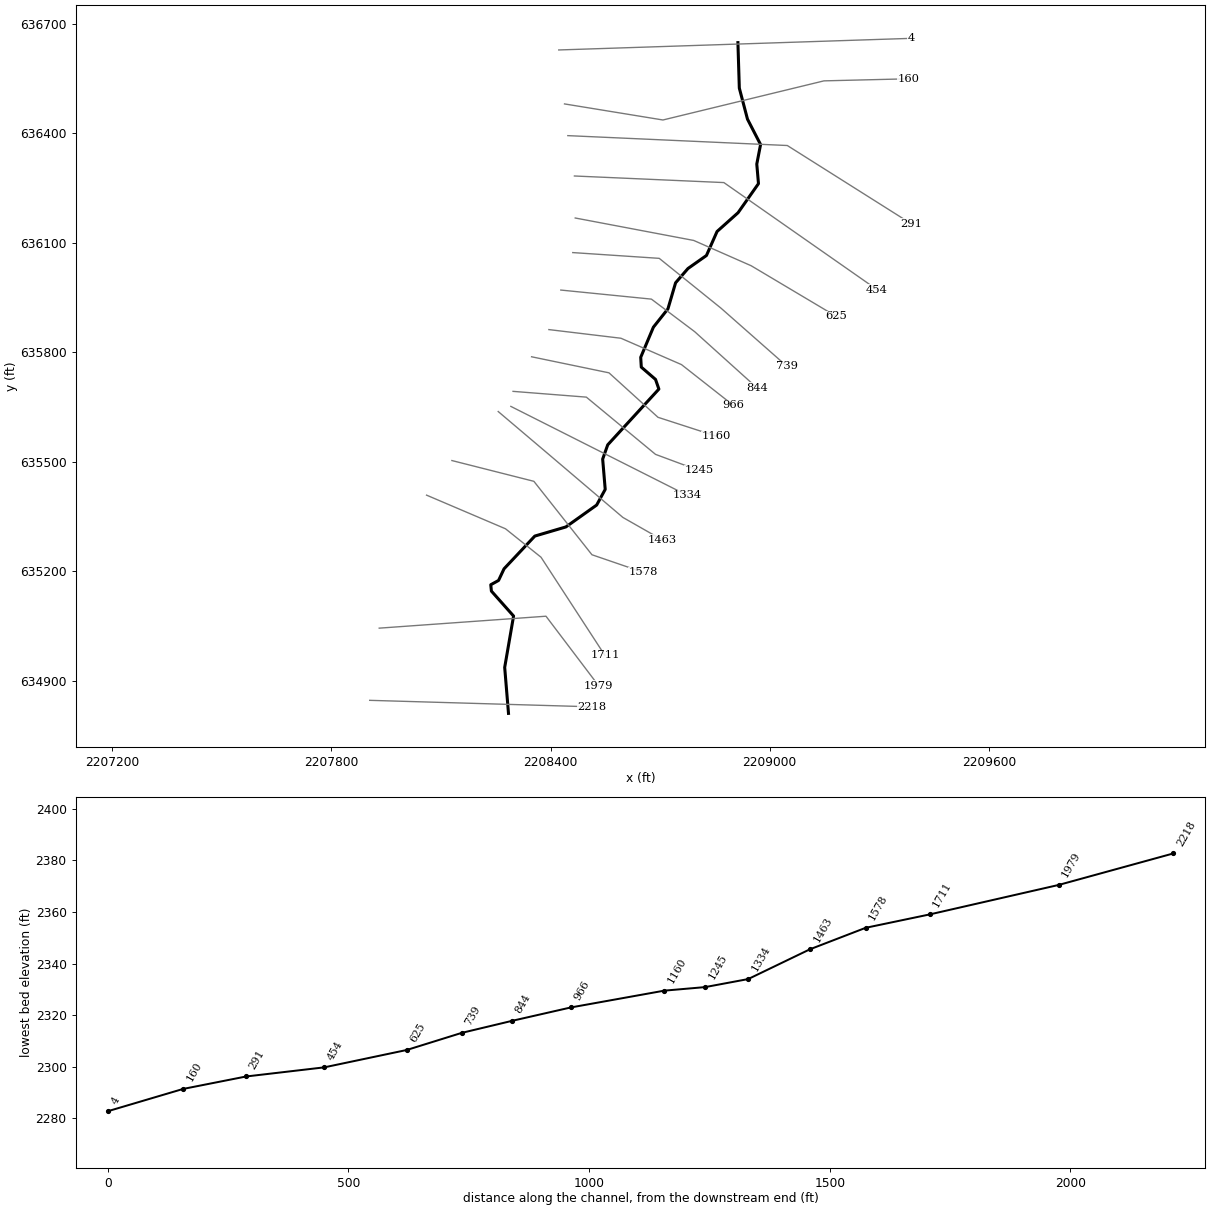
--- LICKRN2.prj (project) ---

Proj Title=LICKRN2
Current Plan=p01
Default Exp/Contr=0,0
English Units
Geom File=g01
Flow File=f01
Plan File=p01
Background Map Layer=Inundation Boundary (P100yr Value_0)
BEGIN DESCRIPTION:
----------MODEL BY WOOD PLC 2022----------
AFH study
Randolph County, WV
HEC-RAS Version: RAS 6.2
Vertical Datum: NAVD88
Projection: NAD 1983 StatePlane West Virginia S FIPS 4702 (US Feet)
Terrain: 1-meter LIDAR (FEMA Region III 3DEP collected 2016-2018)
Land Use: 2019 NLCD
Hydrologic Method:
WV SIR2010-5033 regression equations
Additional Model Notes:
Downstream boundary at Randolph/Upshur county boundary
END DESCRIPTION:
DSS Export Rating Curves= 0
DSS Export Rating Curve Sorted= 0
DSS Export Volume Flow Curves= 0
DXF OffsetX= 0
DXF OffsetY= 0
DXF ScaleX= 0
DXF ScaleY= 0

--- LICKRN2.p01 (plan) ---

Plan Title=Floodplain
Program Version=6.20
Short Identifier=Floodplain
Geom File=g01
Flow File=f01
Subcritical Flow
K Sum by GR= 0
Std Step Tol= 0.01
Critical Tol= 0.01
Num of Std Step Trials= 20
Max Error Tol= 0.3
Flow Tol Ratio= 0.001
Split Flow NTrial= 30
Split Flow Tol= 0.02
Split Flow Ratio= 0.02
Log Output Level= 0
Friction Slope Method= 1
Unsteady Friction Slope Method= 2
Unsteady Bridges Friction Slope Method= 1
Parabolic Critical Depth
Global Vel Dist= 0 , 0 , 0
Global Log Level= 0
CheckData=True
Encroach Param=-1 ,0,0, 0
Mapping Interval=1HOUR
Computation Time Step Use Courant=        0
Computation Time Step Use Time Series=    0
Computation Time Step Count To Double=0
Computation Time Step Max Doubling=0
Computation Time Step Max Halving=0
Computation Time Step Residence Courant=0
Run HTab= 0
Run UNet= 0
Run Sediment= 0
Run PostProcess= 0
Run WQNet= 0
Run RASMapper=-1
UNET Theta= 0
UNET Theta Warmup= 0
UNET ZTol= 0
UNET ZSATol= 0
UNET MxIter= 0
UNET Max Iter WO Improvement= 0
UNET MaxInSteps= 0
UNET DtIC= 0
UNET DtMin= 0
UNET MaxCRTS= 0
UNET WFStab= 0
UNET SFStab= 0
UNET WFX= 1
UNET SFX= 1
UNET Gravity=32.174
UNET 1D Methodology=Finite Difference
UNET DSS MLevel= 1
UNET Pardiso=0
UNET DZMax Abort= 0
UNET Use Existing IB Tables= 0
UNET Froude Reduction=False
UNET Froude Limit= 0
UNET Froude Power= 0
UNET D1 Cores= 0
UNET WindReference=Eulerian
UNET WindDragFormulation=Hsu (1988)
UNET D2 Coriolis=0
UNET D2 Cores= 0
UNET D2 Theta= 1
UNET D2 Theta Warmup= 1
UNET D2 Z Tol= 0.01
UNET D2 Volume Tol= 0.01
UNET D2 Max Iterations= 20
UNET D2 Equation= 0
UNET D2 RampUpFraction=0.1
UNET D2 TimeSlices= 1
UNET D2 Turbulence Formulation=Non-Conservative (original)
UNET D2 Eddy Viscosity=0.3
UNET D2 Transverse Eddy Viscosity=0.1
UNET D2 Smagorinsky Mixing=0
UNET D2 BCVolumeCheck=0
UNET D2 Cores=0
UNET D2 SolverType=PARDISO (Direct)
UNET D2 Minimum Iterations= 2147483647
UNET D2 Maximum Iterations= 2147483647
UNET D2 Restart Number= 10
UNET D2 Relaxation Coeff=1.3
UNET D2 SOR Precondition Iterations= 10
UNET D2 ILUT Maximum Fill= 8
UNET D2 ILUT Tolerance=1E-08
UNET D1D2 MaxIter= 0
UNET D1D2 ZTol=0.01
UNET D1D2 QTol=0.1
UNET D1D2 MinQTol=1
Write IC File= 0
Write IC File at Fixed DateTime=0
Write IC File at Sim End=0
Echo Input=False
Echo Parameters=False
Echo Output=False
Write Detailed= 0
HDF Write Warmup=0
HDF Write Time Slices=0
HDF Flush=0
HDF Compression= 1
HDF Chunk Size= 1
HDF Spatial Parts= 1
HDF Use Max Rows=0
HDF Fixed Rows= 1
Calibration Method= 0
Calibration Iterations= 20
Calibration Max Change=0.05
Calibration Tolerance=0.2
Calibration Maximum=1.5
Calibration Minimum=0.5
Calibration Optimization Method= 1
WQ AD Non Conservative
WQ ULTIMATE=-1
WQ Max Comp Step=1HOUR
WQ Output Interval=15MIN
WQ Output Selected Increments= 0
WQ Output face flow=0
WQ Output face velocity=0
WQ Output face area=0
WQ Output face dispersion=0
WQ Output cell volume=0
WQ Output cell surface area=0
WQ Output cell continuity=0
WQ Output cumulative cell continuity=0
WQ Output face conc=0
WQ Output face dconc_dx=0
WQ Output face courant=0
WQ Output face peclet=0
WQ Output face adv mass=0
WQ Output face disp mass=0
WQ Output cell mass=0
WQ Output cell source sink temp=0
WQ Output nsm pathways=0
WQ Output nsm derived pathways=0
WQ Create Restart=0
WQ Fixed Restart=0
WQ System Summary=0
WQ Write To DSS=0
Sorting and Armoring Iterations= 10
XS Update Threshold= 0.02
Bed Roughness Predictor= 0
Hydraulics Update Threshold= 0.02
Energy Slope Method= 1
Volume Change Method= 1
Sediment Retention Method= 0
Sediment TS Multiplier= 1
Warm Up Method= 0
XS Weighting Method= 0
Number of US Weighted Cross Sections= 1
Number of DS Weighted Cross Sections= 1
Upstream XS Weight=0
Main XS Weight=1
Downstream XS Weight=0
Number of DS XS's Weighted with US Boundary= 1
Upstream Boundary Weight= 1
Weight of XSs Associated with US Boundary= 0
Number of US XS's Weighted with DS Boundary= 1
Downstream Boundary Weight= 0.5
Weight of XSs Associated with DS Boundary= 0.5
Percentile Method= 0
Sediment Output Level= 3
Mass or Volume Output= 0
Output Increment Type= 1
Profile and TS Output Increment= 1
Transport Output Increment 1
XS Output Flag= 0
XS Output Increment= 10
Read HDF5 Sediment Hotstart= 0
Sediment Hotstart Type= 0
Write Gradation File= 0
Read Gradation Hotstart= 0
Write HDF5 File= 1
Write Binary Output= 1
Write DSS Sediment File= 0
DSS Sediment Output Type= 1
SV Curve= 0
Specific Gage Flag= 0
Subcell Erosion Methods= 0
Subcell Deposition Methods= 0
Advection Scheme= 1
Matrix Solver= 0
Implicit Weighting Factor= 1
Maximum Outer Loop Convergence Iterations= 5
Convergence Maximum Absolute= 0.001
Convergence RMSE= 0.0001
Grain Fractions Max Abs Error= 0.001
Max Subgrid Regions= 1
Max Subgrid Length Scale= 3.402823E+38
Initial Layer Thickness= 3.402823E+38
Min Layer Thickness= 3.402823E+38
Max Layer Thickness= 3.402823E+38
Number of Layers= 5

--- LICKRN2.f01 (steady flow) ---

Flow Title=Flow
Program Version=6.20
Number of Profiles= 1
Profile Names=P100yr
River Rch & RM=LICKRN2,Main,2218
     393
Boundary for River Rch & Prof#=LICKRN2,Main            , 1
Up Type= 0
Dn Type= 3
Dn Slope=0.050094
DSS Import GetInterval= 0
DSS Import GetPeak= 0
DSS Import FillOption= 0

--- LICKRN2.g01 (geometry) ---

Geom Title=Geometry
Program Version=6.20

River Reach=LICKRN2         ,Main
Reach XY= 30
     2208284.912      634811.321     2208274.495       634937.19
     2208298.801      635077.815     2208238.095      635146.101
     2208236.407      635163.489     2208257.684       635175.25
     2208272.759      635207.1552208356.95313278  635296.7072212
      2208442.03      635321.738     2208526.231      635381.634
     2208549.703      635424.556     2208542.725      635507.502
     2208556.614      635546.565     2208696.622      635699.142
     2208687.447      635725.592     2208648.457      635759.256
     2208646.891      635786.148     2208681.613      635868.613
     2208721.433      635918.835     2208742.377      635990.141
     2208776.232      636029.203     2208826.847      636064.864
     2208855.901      636130.589     2208913.384      636181.981
     2208969.283       636261.61     2208964.654      636315.174
     2208975.016      636368.638     2208939.193      636438.137
     2208916.857      636523.1272208912.99089384636647.685397037

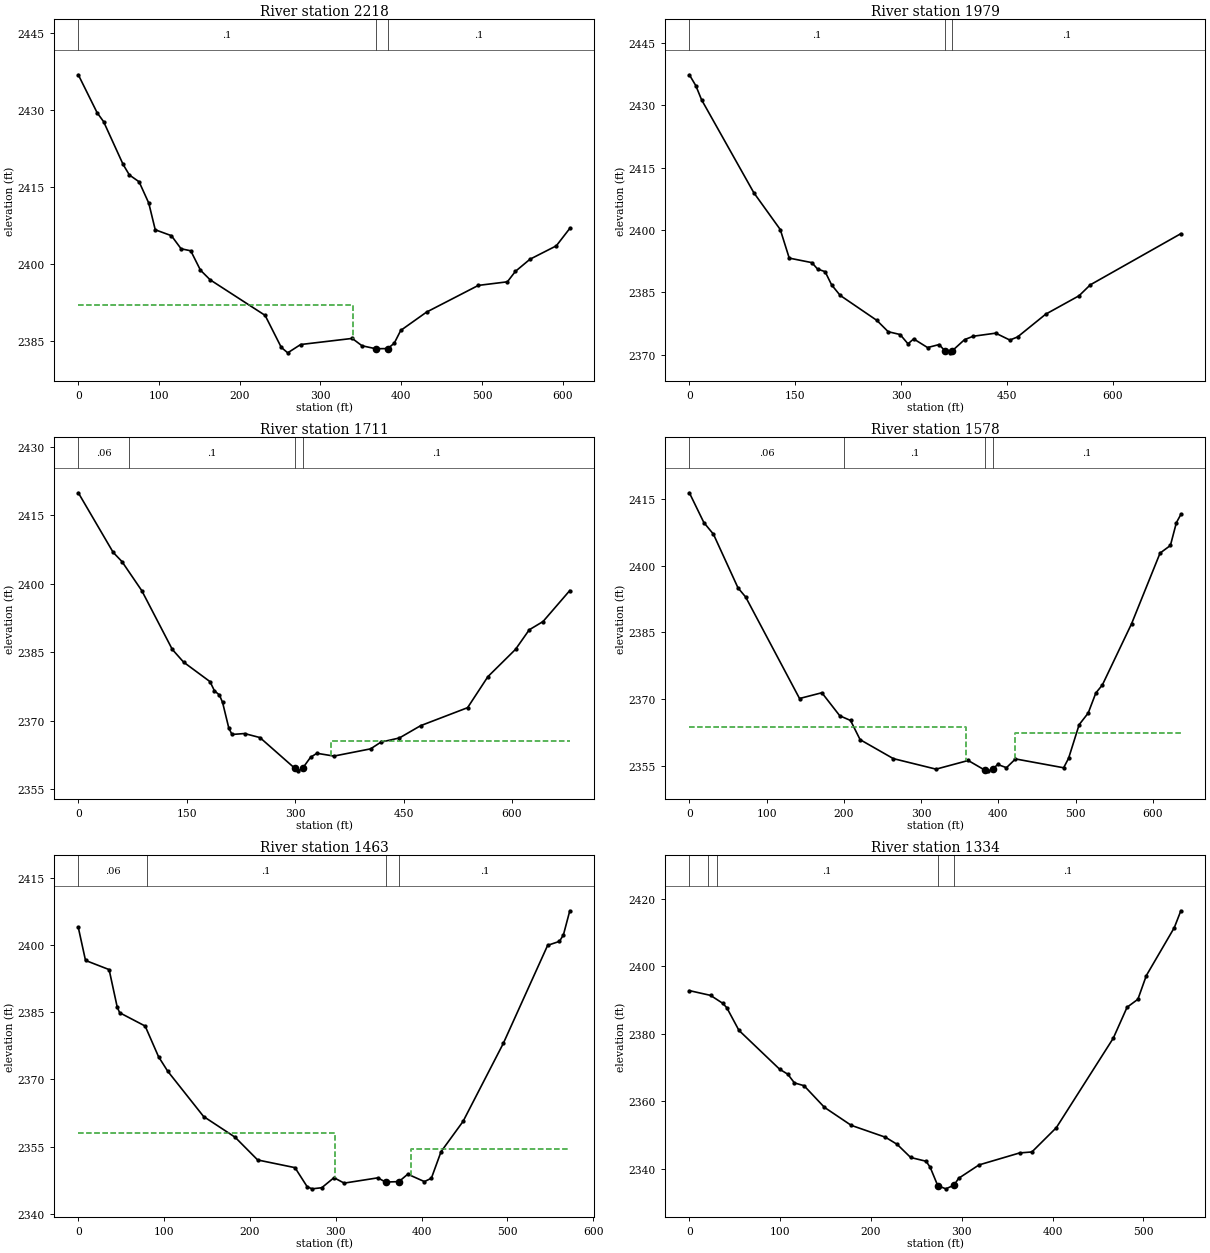
Type RM Length L Ch R = 1 ,2218    ,237.5,238.4,238.3
XS GIS Cut Line= 2
2207904.91817309634847.0282230692208513.44062984 634829.25604102
#Sta/Elev= 30
       0 2436.87    23.3 2429.48    31.3 2427.75    55.5  2419.4    63.3 2417.34
    75.3 2416.02    87.3 2411.86    95.3 2406.67   115.3 2405.52   127.3 2402.97
   139.3 2402.57   151.3  2398.8   163.3 2396.92   231.4 2389.99   251.4 2383.76
   259.4 2382.69   275.4 2384.31   339.3  2385.5   351.4 2384.07   368.3 2383.49
   383.4 2383.52   391.4 2384.58   399.4 2387.06   431.4 2390.63   495.5 2395.83
   531.5 2396.53   541.4 2398.56   559.5 2400.93   592.1 2403.54   608.8 2406.94
#Mann= 3 ,-1,0
       0      .1       0   368.3    .045       0   383.4      .1       0
#XS Ineff= 2 , 0
          340.14  2392.1
Permanent Ineff=
       F       F
Bank Sta=368.3,383.4
XS Rating Curve= 0 ,0
Exp/Cntr(USF)=0,0
Exp/Cntr=0.3,0.1

Type RM Length L Ch R = 1 ,1979    ,270.4,268.1,262.1
XS GIS Cut Line= 3
2207930.94949737635044.6352226812208387.55356416635077.330328698
2208531.86299761634886.796779841
#Sta/Elev= 30
       0  2437.3     9.2 2434.67    17.3  2431.3    91.4 2408.95   128.9  2400.1
   141.6 2393.24   173.7 2392.15   181.7 2390.62   192.5 2389.97   201.7  2386.8
   213.8 2384.28   265.9 2378.26   281.9 2375.55   298.8 2374.87     310 2372.63
     318 2373.82   337.7 2371.74   354.1 2372.46   362.2 2370.97   370.2 2370.47
  372.772370.968   390.2 2373.65   402.5 2374.46   434.3  2375.2   454.4 2373.54
   465.4  2374.3   505.2 2379.76   552.5 2384.19   568.4 2386.81   696.8 2399.11
#Mann= 3 ,-1,0
       0      .1       0   362.2    .045       0  372.77      .1       0
Bank Sta=362.2,372.77
XS Rating Curve= 0 ,0
Exp/Cntr(USF)=0,0
Exp/Cntr=0.3,0.1

Type RM Length L Ch R = 1 ,1711    ,134.6,133,131.2
XS GIS Cut Line= 4
2208060.60250399635408.791058661 2208276.7849515635316.646020072
2208373.98755482 635238.774237072208548.77425934634970.225671056
#Sta/Elev= 30
       0 2419.88    48.2 2406.85    60.4 2404.83    87.8 2398.47     130 2385.62
   145.7 2382.82   182.2 2378.56   188.4 2376.54   195.2 2375.64   199.6 2374.01
   208.2 2368.42   212.6    2367     230  2367.2   251.3 2366.32   299.6 2359.59
   304.5 2359.04   310.9 2359.73   321.3    2362   330.1 2362.88   353.7 2362.27
   404.4 2363.85   418.7 2365.32   444.2 2366.23   473.6 2368.92   538.6 2372.86
   566.7 2379.65   604.9 2385.62   623.9  2389.9     643 2391.71     680 2398.49
#Mann= 4 ,-1,0
       0     .06       0      70      .1       0   299.6    .045       0
   310.9      .1       0
#XS Ineff= 2 , 0
                          349.46         2365.57
Permanent Ineff=
       F       F
Bank Sta=299.6,310.9
XS Rating Curve= 0 ,0
Exp/Cntr(USF)=0,0
Exp/Cntr=0.3,0.1

Type RM Length L Ch R = 1 ,1578    ,113.8,115.7,116.6
XS GIS Cut Line= 4
2208129.95398383635503.494995777 2208354.4150771 635446.63775334
2208513.36912218635245.5976485812208653.59622141635197.525210007
#Sta/Elev= 30
       0 2416.44    18.8 2409.73    31.2 2407.11      63 2395.02    72.9 2392.97
   142.6 2370.13   171.5 2371.43   194.7 2366.24   208.6 2365.19     221 2360.87
     264  2356.6   319.3 2354.23   360.9 2356.18382.95672353.949   386.4 2353.85
392.40032354.175     399 2355.29   410.4 2354.56   422.1 2356.53   484.4 2354.54
   490.8 2356.67   504.5 2364.25   516.2 2366.86   526.1 2371.38   534.5 2373.17
   572.3 2386.95   609.2 2402.86   622.6 2404.58   630.3  2409.7   636.1 2411.56
#Mann= 4 ,-1,0
       0     .06       0     200      .1       0382.9567    .045       0
392.4003      .1       0
#XS Ineff= 2 , 0
          358.29 2363.67  421.52         2362.31
Permanent Ineff=
       F       F
Bank Sta=382.9567,392.4003
XS Rating Curve= 0 ,0
Exp/Cntr(USF)=0,0
Exp/Cntr=0.3,0.1

Type RM Length L Ch R = 1 ,1463    ,125.9,128.3,128.9
XS GIS Cut Line= 4
2208256.77314009635637.6568007792208400.72436917635515.640581481
2208598.07141842635347.7559120872208706.61270218635285.902556736
#Sta/Elev= 30
       0 2404.01     8.4 2396.63    35.9 2394.58    45.3 2386.23    48.2 2384.93
    77.9 2381.95    93.5 2375.09   104.1 2371.87     146 2361.71   182.7 2357.08
     209 2351.99   252.5 2350.27   266.7    2346   272.4 2345.53   283.7 2345.78
   297.9 2348.02   309.8 2346.81     349 2347.99357.97182347.048373.59172347.146
   383.9 2348.81   403.3 2347.15   411.4  2347.9   422.7 2353.85   448.3 2360.61
   495.2 2378.06   546.9 2400.01   560.7  2400.9   565.3 2402.37   572.7 2407.74
#Mann= 4 ,-1,0
       0     .06       0      80      .1       0357.9718    .045       0
373.5917      .1       0
#XS Ineff= 2 , 0
          299.45 2357.92  387.73         2354.36
Permanent Ineff=
       F       F
Bank Sta=357.9718,373.5917
XS Rating Curve= 0 ,0
Exp/Cntr(USF)=0,0
Exp/Cntr=0.3,0.1

Type RM Length L Ch R = 1 ,1334    ,91.7,89.3,88
XS GIS Cut Line= 2
2208291.38794003635651.7299492742208774.67450075635408.056053115
#Sta/Elev= 30
       0 2392.78    23.3 2391.37    36.7 2389.03    41.2 2387.72    54.6 2380.99
    99.4 2369.47   108.4 2367.99   115.7 2365.41   126.3 2364.58   148.7 2358.17
   178.2 2352.83   215.9  2349.3   228.8 2347.19   243.7 2343.29   260.7 2342.17
   265.2 2340.38   273.5 2334.95   282.4 2333.99   291.4 2335.08   296.5 2337.11
   318.9 2341.08   363.7 2344.64   377.2 2344.93   404.1 2352.13   466.8 2378.67
     482 2387.85   493.9 2390.21   503.2 2397.24     534 2411.46   541.2 2416.46
#Mann= 5 ,-1,0
       0      .1       0      20     .06       0      30      .1       0
   273.5    .045       0   291.4      .1       0
Bank Sta=273.5,291.4
XS Rating Curve= 0 ,0
Exp/Cntr(USF)=0,0
Exp/Cntr=0.3,0.1

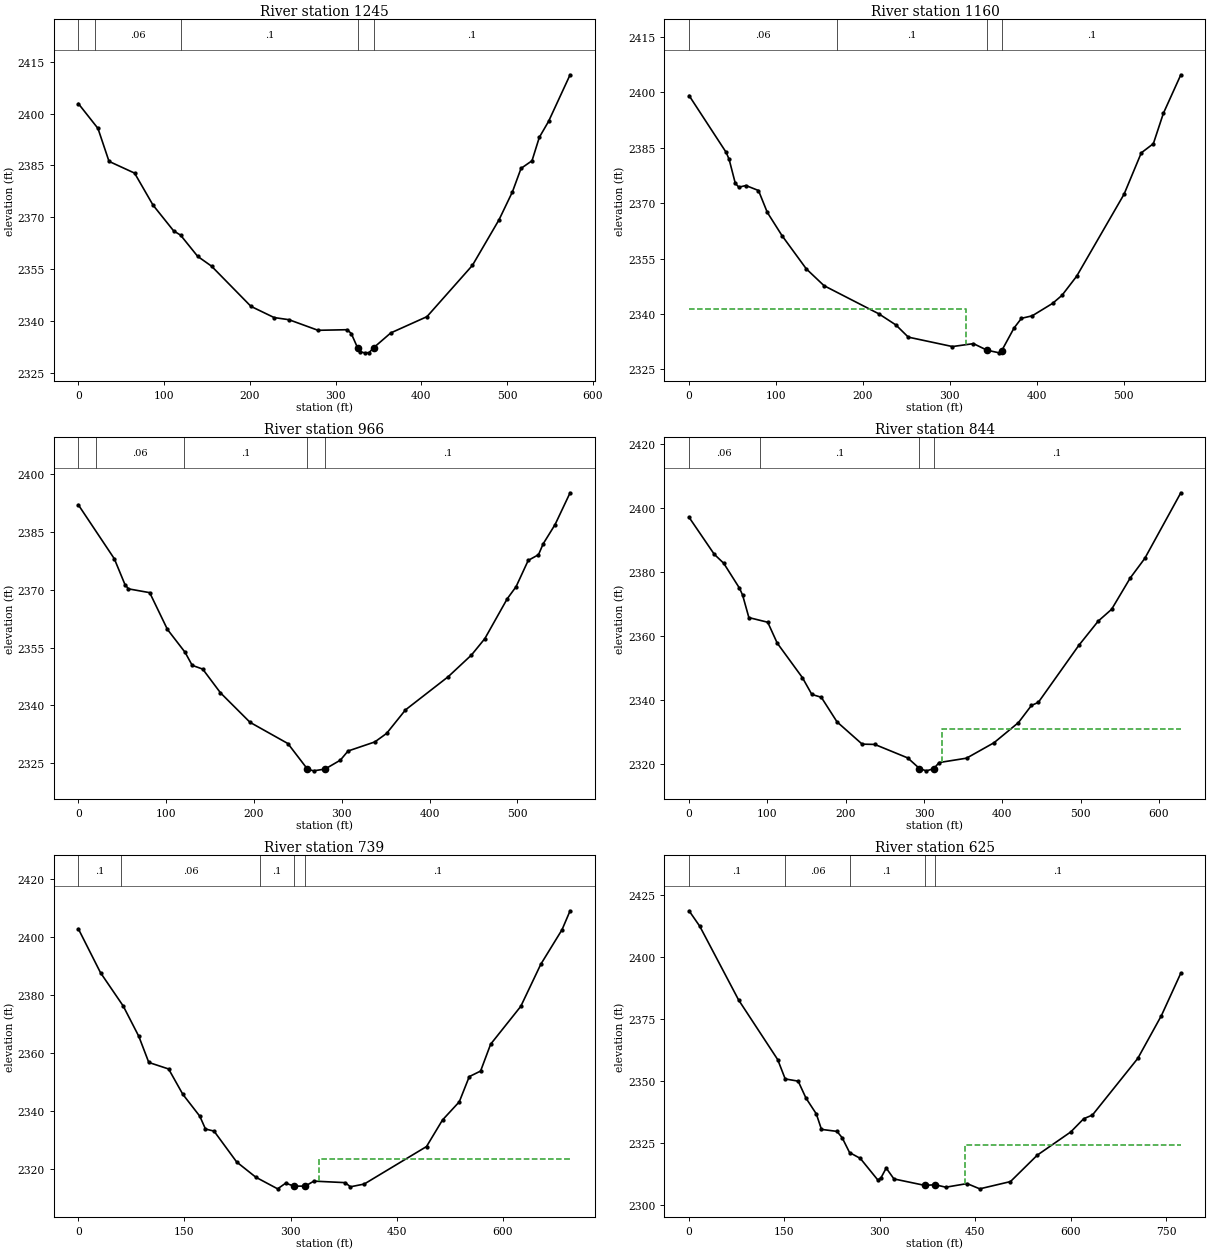
Type RM Length L Ch R = 1 ,1245    ,85.3,85,84.4
XS GIS Cut Line= 4
2208297.36016825635692.9002557732208498.04047415635677.116411489
2208687.44660555635520.4053860982208805.82543768635476.436105593
#Sta/Elev= 30
       0 2402.88    22.9  2395.7    35.8 2386.18    65.6 2382.79    87.1 2373.55
   111.2 2366.09   119.2 2364.88   139.2 2358.74   155.3 2355.92   201.3  2344.3
   228.3 2341.07   245.6 2340.45   279.5 2337.39   313.6 2337.56   318.3 2336.44
  325.582332.353   328.7 2331.17   333.9 2330.88   339.1 2330.96   344.2 2332.33
   364.3 2336.63   406.5 2341.33   459.5 2356.14   490.6 2369.34   506.2  2377.4
   516.2 2384.15     529 2386.36   537.5 2393.11   548.3 2397.73   573.4 2411.19
#Mann= 5 ,-1,0
       0      .1       0      20     .06       0     120      .1       0
  325.58    .045       0   344.2      .1       0
Bank Sta=325.58,344.2
XS Rating Curve= 0 ,0
Exp/Cntr(USF)=0,0
Exp/Cntr=0.3,0.1

Type RM Length L Ch R = 1 ,1160    ,187.6,194.4,191.2
XS GIS Cut Line= 4
2208348.09395345635787.6033214772208560.04843383635743.634040972
2208694.21111025635621.8729564952208854.30438798635570.011753848
#Sta/Elev= 30
       0 2399.14    42.7 2383.75    46.1 2381.87    53.2 2375.39    57.3 2374.33
    65.4 2374.78    79.9 2373.43      90 2367.53     107 2361.21   134.9 2352.23
   155.3 2347.68   218.3 2340.07     238 2337.05   252.3 2333.75   303.1  2331.2
   327.3 2331.99   342.9 2330.21     357  2329.5   359.9 2330.13     374 2336.23
   382.5 2338.84   394.9 2339.52   418.3 2342.88   429.1 2345.05     446 2350.22
   500.6 2372.44   520.4 2383.62   534.3 2386.11   545.8 2394.31   565.9 2404.75
#Mann= 4 ,-1,0
       0     .06       0     170      .1       0   342.9    .045       0
   359.9      .1       0
#XS Ineff= 2 , 0
          319.13 2341.37
Permanent Ineff=
       F       F
Bank Sta=342.9,359.9
XS Rating Curve= 0 ,0
Exp/Cntr(USF)=0,0
Exp/Cntr=0.3,0.1

Type RM Length L Ch R = 1 ,966     ,123.2,121.6,118.6
XS GIS Cut Line= 4
 2208395.4454863635862.0128731012208592.74353985635838.337106675
2208758.47390483635766.1823899492208900.52850339635654.568062512
#Sta/Elev= 30
       0  2392.1      41 2378.08    53.1 2371.39    57.1 2370.26    81.3 2369.27
   101.5 2359.72   121.6 2353.77   129.7 2350.39   141.7 2349.41   161.9 2343.25
   195.6 2335.58   238.7 2330.07     2612323.423   267.9 2322.98     281 2323.44
   298.4 2325.75   307.2 2328.13   337.7 2330.49   351.1  2332.7   372.6 2338.81
   421.3 2347.44   447.8 2353.08     463 2357.33   488.5 2367.68   498.6 2370.83
   512.4 2377.65   524.1 2379.13   529.5 2381.98     543 2386.96   560.1 2395.22
#Mann= 5 ,-1,0
       0      .1       0      20     .06       0     120      .1       0
     261    .045       0     281      .1       0
Bank Sta=261,281
XS Rating Curve= 0 ,0
Exp/Cntr(USF)=0,0
Exp/Cntr=0.3,0.1

Type RM Length L Ch R = 1 ,844     ,105.1,104.9,105.1
XS GIS Cut Line= 4
2208428.14059232635970.2449481922208676.17243106635945.441764317
2208794.55126319635856.3757858572208965.91871542635701.919595364
#Sta/Elev= 30
       0  2397.1    32.2 2385.54    44.3 2382.72    64.4 2374.94    68.4 2372.77
    76.4 2365.74   100.5 2364.28   112.6 2357.76   144.8 2346.95   156.8 2341.71
   168.9 2340.82     189 2333.12   221.1 2326.16   237.2 2326.07   279.3 2321.85
   294.3 2318.54   302.9 2317.81   312.3 2318.44   319.4  2320.4   354.4 2321.77
   389.5  2326.6   420.7  2332.9   437.3 2338.26   446.1 2339.22   497.8 2357.05
   522.6 2364.64   539.7 2368.33   563.5 2378.13   582.1 2384.26   628.1 2404.77
#Mann= 4 ,-1,0
       0     .06       0      90      .1       0   294.3    .045       0
   312.3      .1       0
#XS Ineff= 2 , 0
                          322.59         2331.03
Permanent Ineff=
       F       F
Bank Sta=294.3,312.3
XS Rating Curve= 0 ,0
Exp/Cntr(USF)=0,0
Exp/Cntr=0.3,0.1

Type RM Length L Ch R = 1 ,739     ,111.9,114,116.4
XS GIS Cut Line= 4
2208460.83569833636072.8399360372208697.59336259636057.056091754
2208866.70597992635920.6385804422209047.09277174635761.672720153
#Sta/Elev= 30
       0 2402.91    31.4 2387.73    63.5 2376.23    85.5 2365.77    99.6 2356.76
   127.6 2354.51   147.7 2345.76   171.7  2338.2   179.7 2333.78   191.8 2333.06
   223.8  2322.4   250.9 2317.14   281.7 2313.13   293.1  2315.1   304.5 2314.07
   320.62314.058   332.9 2315.79   377.2 2315.27   384.5 2313.83     404 2314.78
   492.1 2327.73   514.7 2336.91   538.4 2343.17   552.5 2351.87   568.5 2353.79
   582.7 2363.06   625.3 2376.12   653.6 2390.66   683.6 2402.58     695 2409.12
#Mann= 5 ,-1,0
       0      .1       0      60     .06       0  257.28      .1       0
   304.5    .045       0   320.6      .1       0
#XS Ineff= 2 , 0
                          339.64         2323.59
Permanent Ineff=
       F       F
Bank Sta=304.5,320.6
XS Rating Curve= 0 ,0
Exp/Cntr(USF)=0,0
Exp/Cntr=0.3,0.1

Type RM Length L Ch R = 1 ,625     ,172.9,171.3,168.6
XS GIS Cut Line= 4
2208467.60020303636167.5430017412208791.99860847636106.082936997
2208949.37450778636036.767950059 2209182.3828656635898.090231465
#Sta/Elev= 30
       0  2418.8    16.9 2412.53    77.9 2382.79   139.4  2358.7   151.2 2350.89
   171.6    2350   183.9 2343.13   200.1 2336.78   208.2 2330.52   232.6 2329.71
   240.8 2327.14   252.4 2321.16   269.3  2318.8   296.9 2310.06   301.9 2311.01
     310  2314.9   322.2 2310.51  370.392307.921   387.2 2308.15   403.8 2307.17
   437.2 2308.63   457.1 2306.51   505.4 2309.44   547.6 2320.12   600.2 2329.48
   620.6 2334.83   634.3 2336.31   705.6 2359.18   742.8 2376.49   773.3 2393.62
#Mann= 5 ,-1,0
       0      .1       0   151.2     .06       0   252.4      .1       0
  370.39    .045       0   387.2      .1       0
#XS Ineff= 2 , 0
                          434.24         2324.38
Permanent Ineff=
       F       F
Bank Sta=370.39,387.2
XS Rating Curve= 0 ,0
Exp/Cntr(USF)=0,0
Exp/Cntr=0.3,0.1

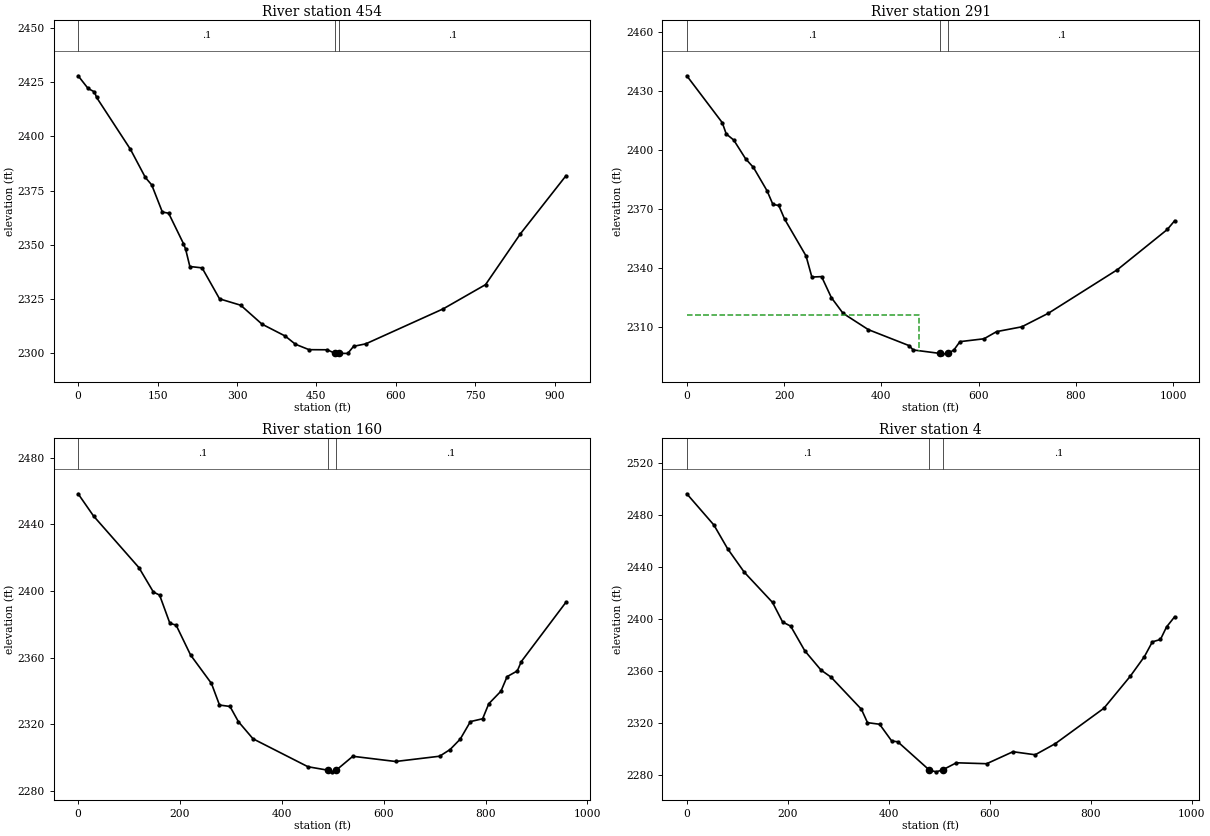
Type RM Length L Ch R = 1 ,454     ,159,162.4,164.5
XS GIS Cut Line= 3
2208465.34536813636282.5395815252208874.59790206636264.500902343
2209293.99719304 635971.37236564
#Sta/Elev= 30
       0 2427.93    18.8 2422.08    30.9  2420.5    34.9 2417.95    98.9    2394
     127 2381.05     139 2377.64     159 2365.17     171 2364.56     199 2350.54
     203 2348.03     211 2340.03   234.1  2339.4   267.1 2325.12   307.1 2322.18
   347.2 2313.47   391.1 2307.98   410.3 2304.21   436.1  2301.7   470.6 2301.65
   484.8 2300.04   489.7 2299.78   492.3 2300.01   509.2 2299.97   520.2 2303.24
   543.3 2304.39   689.7 2320.54   769.4 2331.67   835.4 2355.15   921.3 2381.86
#Mann= 3 ,-1,0
       0      .1       0   484.8    .045       0   492.3      .1       0
Bank Sta=484.8,492.3
XS Rating Curve= 0 ,0
Exp/Cntr(USF)=0,0
Exp/Cntr=0.3,0.1

Type RM Length L Ch R = 1 ,291     ,128.2,131,133.6
XS GIS Cut Line= 3
2208447.30668895636393.0264915132209048.22018919 636365.96847274
2209387.57284129636151.759157457
#Sta/Elev= 30
       0 2437.56    72.9 2413.74    81.1 2407.98    96.5  2404.9     121 2395.32
     137 2390.98     165  2379.1     177 2372.18   189.1 2371.64   201.1  2364.7
   245.1    2346   257.1 2335.27   277.1 2335.48   297.2  2324.8   321.2 2316.83
   373.2 2308.54   457.3 2300.38   465.3 2298.22   519.92296.467   525.4 2296.24
   537.8 2296.44   549.4 2298.32   561.4 2302.43   610.9 2303.89   636.9 2307.54
   688.6 2309.97   743.4 2316.89   885.3 2339.04   987.7 2359.44  1002.8 2363.88
#Mann= 3 ,-1,0
       0      .1       0   519.9    .045       0   537.8      .1       0
#XS Ineff= 2 , 0
           476.5 2315.88
Permanent Ineff=
       F       F
Bank Sta=519.9,537.8
XS Rating Curve= 0 ,0
Exp/Cntr(USF)=0,0
Exp/Cntr=0.3,0.1

Type RM Length L Ch R = 1 ,160     ,157.8,156.5,154.5
XS GIS Cut Line= 4
2208438.28734936636479.8376350742208707.74011963636435.868354569
2209148.56034214 636542.973012212209379.68091915636548.610099455
#Sta/Elev= 30
       0 2458.25    30.3 2444.91   119.4 2413.94   147.8 2399.29     160 2397.44
   180.2 2380.52   192.4 2379.46   220.8 2361.52   261.8 2344.45   277.6 2331.49
   298.2 2330.64   314.6 2321.57   343.4 2311.24   451.3 2294.47   491.6 2292.33
   498.8 2291.41   506.3 2292.28   539.4 2300.74   623.4 2297.62   709.8 2300.78
   730.3 2304.78   750.3 2311.05   770.3 2321.56   794.3 2323.26   806.3 2332.25
   830.3 2339.83   842.3 2348.53   862.3 2351.95   870.3  2357.6   957.9 2393.18
#Mann= 3 ,-1,0
       0      .1       0   491.6    .045       0   506.3      .1       0
Bank Sta=491.6,506.3
XS Rating Curve= 0 ,0
Exp/Cntr(USF)=0,0
Exp/Cntr=0.3,0.1

Type RM Length L Ch R = 1 ,4       ,,,
XS GIS Cut Line= 2
2208422.46272085636627.5644286692209388.25346795636659.398614369
#Sta/Elev= 30
       0 2496.19    53.7 2472.21    80.7 2454.11   113.8 2436.01   169.8 2412.81
   189.8 2397.76   205.8 2394.59   233.8 2375.63   265.9 2360.86   285.7 2355.46
   345.9 2330.78   357.9 2320.53   381.9 2319.29   405.9 2306.43   417.9 2305.83
   480.62284.053     494 2282.77   506.9  2284.3     534 2289.72     594    2289
   646.1 2298.21   690.1 2295.87   730.1 2304.45   826.2 2331.59   878.2 2356.04
   906.5 2371.27   922.2 2382.55   938.2 2384.36   950.2 2393.94   966.3 2401.79
#Mann= 3 ,-1,0
       0      .1       0   480.6    .045       0   506.9      .1       0
Bank Sta=480.6,506.9
XS Rating Curve= 0 ,0
Exp/Cntr(USF)=0,0
Exp/Cntr=0.3,0.1
LCMann Table=0

Chan Stop Cuts=-1
Use User Specified Reach Order=0
Composite Channel Slope=5